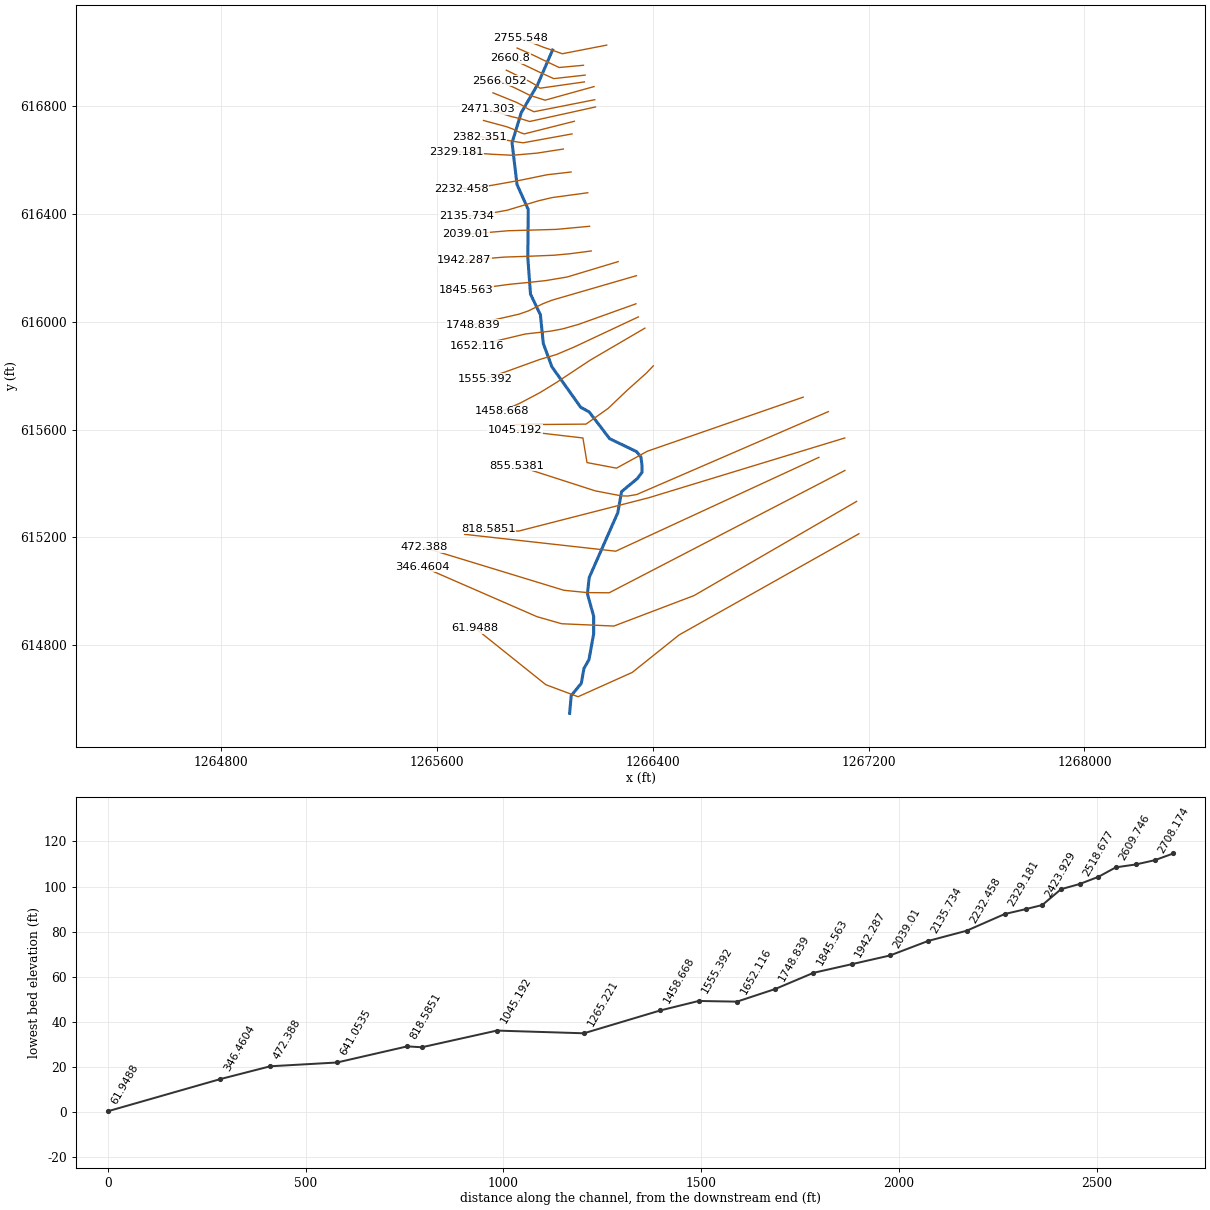
--- 511_ras.prj (project) ---

Proj Title=511
Current Plan=p01
Default Exp/Contr=0.3,0.1
English Units
Geom File=g01
Flow File=f01
Plan File=p01
Y Axis Title=Elevation
X Axis Title(PF)=Main Channel Distance
X Axis Title(XS)=Station
BEGIN DESCRIPTION:
RFD model 511 exported to HEC-RAS
END DESCRIPTION:

--- 511_ras.p01 (plan) ---

Plan Title=Plan 01
Program Version=4.10
Short Identifier=Plan 01
Geom File=g01
Flow File=f01
Subcritical Flow
Calc Critical at every XS
Secant Critical Depth

--- 511_ras.f01 (steady flow) ---

Flow Title=Flow 01
Program Version=5.01
Number of Profiles= 5
Profile Names=10yr,25yr,50yr,100yr,500yr
River Rch & RM=511,27,2755.548
  362.24  428.48  509.84  539.17  625.33
River Rch & RM=511,27,2471.303
  371.71  441.34   525.6  557.96   650.3
River Rch & RM=511,27,2382.351
  374.48  445.12  530.22  563.48  657.67
River Rch & RM=511,27,2135.734
  413.55  498.73  596.04   642.8  764.49
River Rch & RM=511,27,1942.287
  424.37  513.72  614.48  665.22  795.05
River Rch & RM=511,27,1845.563
  426.64  516.86  618.35  669.94   801.5
River Rch & RM=511,27,1748.839
  429.63  521.02  623.47  676.18  810.04
River Rch & RM=511,27,1652.116
  440.57  536.26  642.24  699.14  841.54
River Rch & RM=511,27,1458.668
  449.04  548.08  656.82  717.02  866.19
River Rch & RM=511,27,1265.221
  453.18  553.88  663.97  725.81  878.34
River Rch & RM=511,27,1045.192
  459.28  562.44  674.53  738.82  896.36
Boundary for River Rch & Prof#=511,27,1
Up Type= 0
Dn Type= 2
Boundary for River Rch & Prof#=511,27,2
Up Type= 0
Dn Type= 2
Boundary for River Rch & Prof#=511,27,2
Up Type= 0
Dn Type= 2
Boundary for River Rch & Prof#=511,27,2
Up Type= 0
Dn Type= 2
Boundary for River Rch & Prof#=511,27,2
Up Type= 0
Dn Type= 2

--- 511_ras.g01 (geometry) ---

Geom Title=511
Program Version=4.10

River Reach=511,27
Reach XY= 30
1266029.35500809617005.8801428191265974.35502056616878.380182269
 1265913.5217021616774.2135483311265879.35504228616662.546915787
1265897.68836568616507.546961311 1265939.3550173 616415.04698757
1265937.68834597616237.5470402671265947.68833901616101.713747001
1265984.35499259616025.0471020281265995.18831962615918.380466746
1266026.85497441615832.5471579851266133.52160521615682.547199349
1266165.18826205615665.0472036721266241.02157008615565.880564218
1266340.18820607615518.3805754071266356.85486724615498.380580886
1266361.02153168615464.2139242461266361.02153103615441.713930899
1266343.52153549615418.3806049841266285.18821799615370.047287741
1266271.02155321615291.7139781171266165.18824409615051.714052438
1266158.52157761614991.7140704441266181.85490159614907.547428119
1266181.85489973614844.2141136081266164.35490208614747.547476139
1266145.57135675614714.5644461941266136.02157456614660.047502941
1266098.52158429614614.2141843481266092.68825072614548.380870703

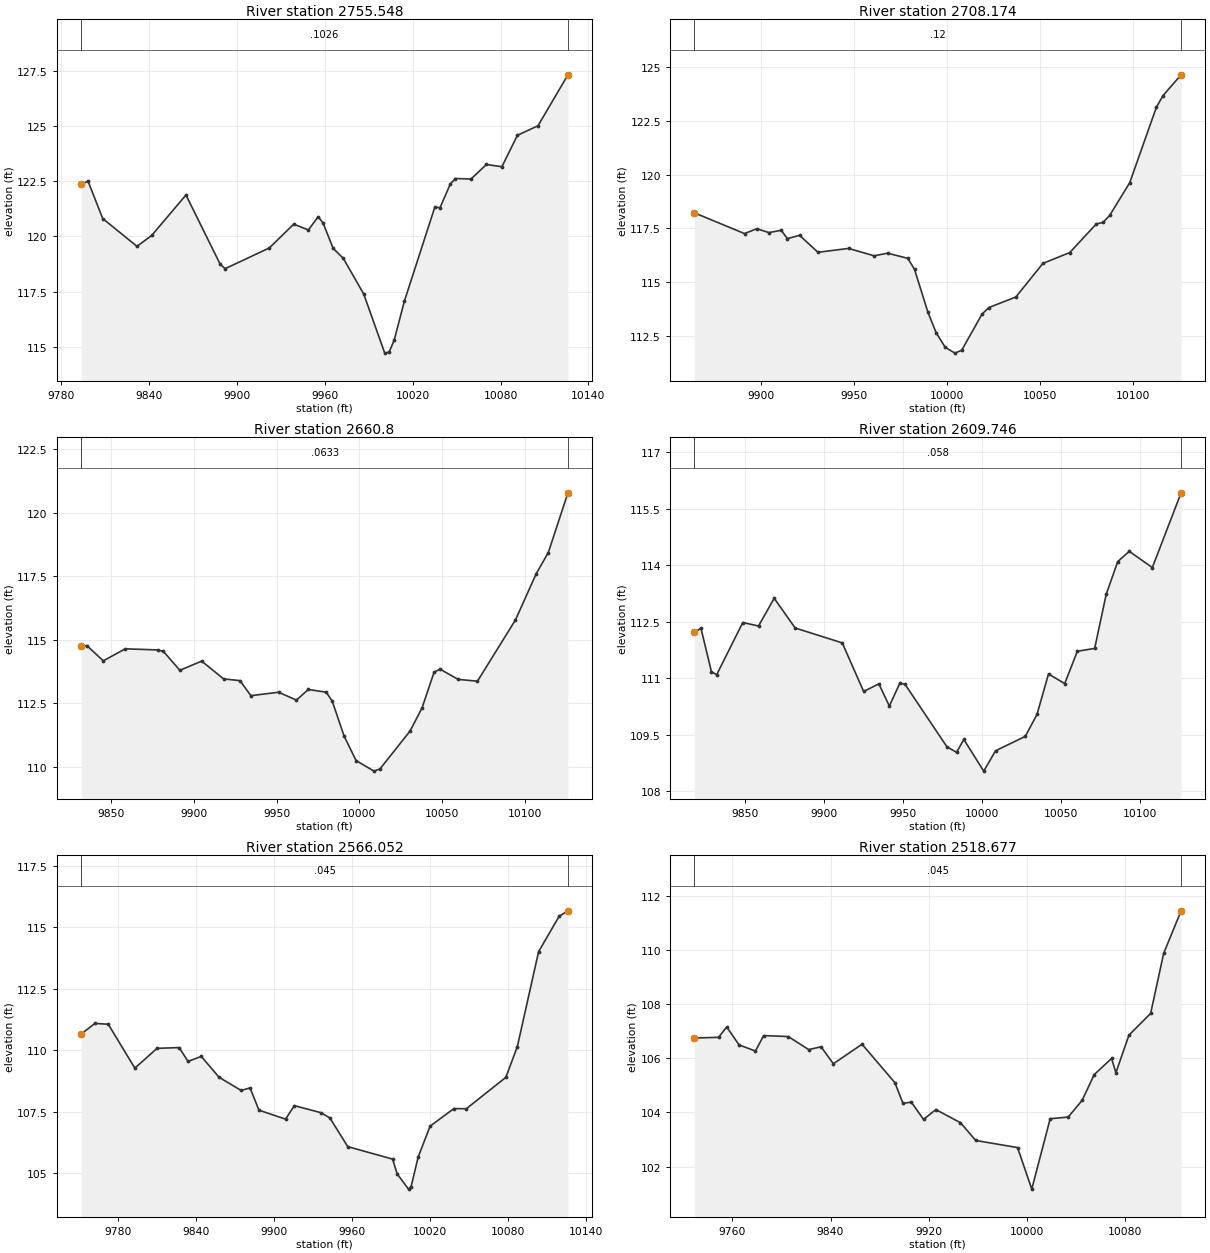
Type RM Length L Ch R = 1 ,2755.548,47.374000,47.374000,47.374000
XS GIS Cut Line= 6
1266229.95222178617024.1132819351266065.65546221616992.191652894
1266030.00745937617004.6254287661266028.10029402617005.227691576
 1265996.3853592617015.9871621431265911.13366261617049.230961621
#Sta/Elev= 30
9793.877122.36069798.494122.51059808.521120.81369831.916119.55399841.943120.0461
9865.338  121.889888.733118.73749892.075118.54249922.155119.47869938.866120.5584
9948.893120.29539955.577120.89969958.919120.60789965.776119.46269972.726119.0084
9986.624117.3963   10001114.715410003.97114.764310007.43115.302310014.36117.0643
10035.16121.331610038.68121.299610045.72122.376610049.25122.626610059.81122.6045
10070.37123.262110080.94123.1606 10091.5 124.58410105.59125.018910125.99 127.325
#Mann= 3 , 0 , 0
9793.877  0.1026       09793.877  0.1026       010125.99  0.1026       0
#XS Ineff= 2 , 0
       09962.986        10026.34       0
Bank Sta=9793.877,10125.99
Exp/Cntr=0.3,0.1

Type RM Length L Ch R = 1 ,2708.174,47.374000,47.374000,47.374000
XS GIS Cut Line= 6
1266144.01472175616949.4605041741266053.98699334616941.205172598
 1266013.6284548616960.1346875731266011.82943851616961.008495539
1265958.36925301616986.746178225 1265898.2744289617013.206595719
#Sta/Elev= 30
9864.017118.22099890.993117.25719897.582117.48259904.171117.3033 9910.76117.4119
9914.055117.02149920.644117.17629930.528116.38679947.001116.56689960.754116.2239
9968.002116.34469978.873116.10659982.497115.59499989.745113.59319994.115112.6519
    9999111.970710004.27111.697410007.91111.832410018.83113.508710022.47113.8162
10037.04114.3066 10051.6115.867910066.08116.376510080.42  117.71   10084117.7744
10087.59118.105610098.34119.620610112.68123.126510116.27123.6745   10126124.6398
#Mann= 3 , 0 , 0
9864.017    0.12       09864.017    0.12       0   10126    0.12       0
#XS Ineff= 2 , 0
       0 9959.61        10034.39       0
Bank Sta=9864.017,10126
Exp/Cntr=0.3,0.1

Type RM Length L Ch R = 1 ,  2660.8,51.054000,51.054000,51.054000
XS GIS Cut Line= 5
1266150.09111065616913.002170846 1266033.7716662616899.981337517
1265988.28752497 616920.643388481265986.40793809616921.326874658
1265873.51759213616974.940443814
#Sta/Elev= 30
9831.997114.7391 9835.43114.76369845.334114.16619858.539114.63979878.347114.5958
9881.648114.53779891.552113.79479904.758114.15539917.963113.45759927.867113.3871
 9934.47112.79649951.153112.93159961.964112.62329969.171113.03979979.981112.9335
9983.584112.58399990.791111.20419997.998110.244510008.81109.827410012.44109.9154
 10030.6111.403310037.86112.315610045.13113.720710048.76113.838910059.65113.4366
10071.33113.366710094.27115.774910106.87117.601210114.13118.428910125.97 120.777
#Mann= 3 , 0 , 0
9831.997  0.0633       09831.997  0.0633       010125.97  0.0633       0
#XS Ineff= 2 , 0
       0 9955.97        10033.58       0
Bank Sta=9831.997,10125.97
Exp/Cntr=0.3,0.1

Type RM Length L Ch R = 1 ,2609.746,43.694100,43.694100,43.694100
XS GIS Cut Line= 6
1266147.48694399616887.8285597261265983.15962783616864.489188448
1265970.62266904616873.0794983061265964.73196608616877.656586498
1265943.31370333616889.6769635981265858.01577052 616931.36123541
#Sta/Elev= 30
9817.973112.21139822.102112.3235 9828.73 111.1749832.044 111.0879848.613112.4749
9858.554112.38229868.495113.1186 9881.75112.32979911.574111.93439925.142 110.644
 9934.77110.84679941.398110.25759948.025110.86289951.339110.83479977.849109.1765
 9983.95109.02859988.559 109.37110001.15108.529810008.66109.070210027.47109.4525
10034.88110.033310042.18111.110110052.42110.853310060.44111.7117 10071.4111.7877
 10078.7113.2218   10086114.091810093.31114.365510107.91113.932710126.12115.9175
#Mann= 3 , 0 , 0
9817.973   0.058       09817.973   0.058       010126.12   0.058       0
#XS Ineff= 2 , 0
       09986.442        10040.07       0
Bank Sta=9817.973,10126.12
Exp/Cntr=0.3,0.1

Type RM Length L Ch R = 1 ,2566.052,47.374100,47.374100,47.374100
XS GIS Cut Line= 6
1266183.07722178616870.4674486071266001.65361068616820.120226398
1265945.76335526 616837.926317141265943.98692003616838.845163018
1265890.80568793616865.1178805381265830.83999348616891.897606716
#Sta/Elev= 30
9752.062 110.6599762.597111.08959772.811 111.055 9793.24109.26999810.264110.0736
9827.288110.10679834.098 109.5449844.312109.74629857.932108.89919874.956108.3608
9881.765108.46759888.575107.56049909.004107.19639915.814 107.7439936.243107.4577
9943.083107.24469956.856106.07719991.289105.56989994.733104.9747 10003.5104.3493
10005.46104.4403 10010.9105.6498 10020.1106.9102 10038.4107.625310047.94107.6195
10078.32108.8961 10087.1110.142610103.47114.009110119.28115.448310125.99115.6672
#Mann= 3 , 0 , 0
9752.062   0.045       09752.062   0.045       010125.99   0.045       0
#XS Ineff= 2 , 0
       09966.235        10035.58       0
Bank Sta=9752.062,10125.99
Exp/Cntr=0.3,0.1

Type RM Length L Ch R = 1 ,2518.677,47.374000,47.374000,47.374000
XS GIS Cut Line= 6
1266185.68138841616821.8563375171265960.53432867616777.345983207
1265938.04993689 616788.033604921265914.02330783616802.685286418
1265893.88988417616812.7888931631265808.70646712616847.304216713
#Sta/Elev= 30
9728.983106.75569748.674106.78119755.363107.16499765.396   106.59778.773106.2745
9785.462106.84579805.528106.81029822.249106.32649832.282106.43239842.315105.8025
9865.726 106.526 9892.48105.10579899.169104.33279905.858104.38669915.891103.7438
9925.924104.1065 9945.99103.62199958.488 102.9639992.574102.701110004.17101.1626
10019.19103.768310033.87103.830210045.23104.446710055.12105.402710069.28105.9998
10072.82105.473410083.44106.862510101.14107.665810111.76109.887810125.97111.4632
#Mann= 3 , 0 , 0
9728.983   0.045       09728.983   0.045       010125.97   0.045       0
#XS Ineff= 2 , 0
       09962.333        10034.11       0
Bank Sta=9728.983,10125.97
Exp/Cntr=0.3,0.1

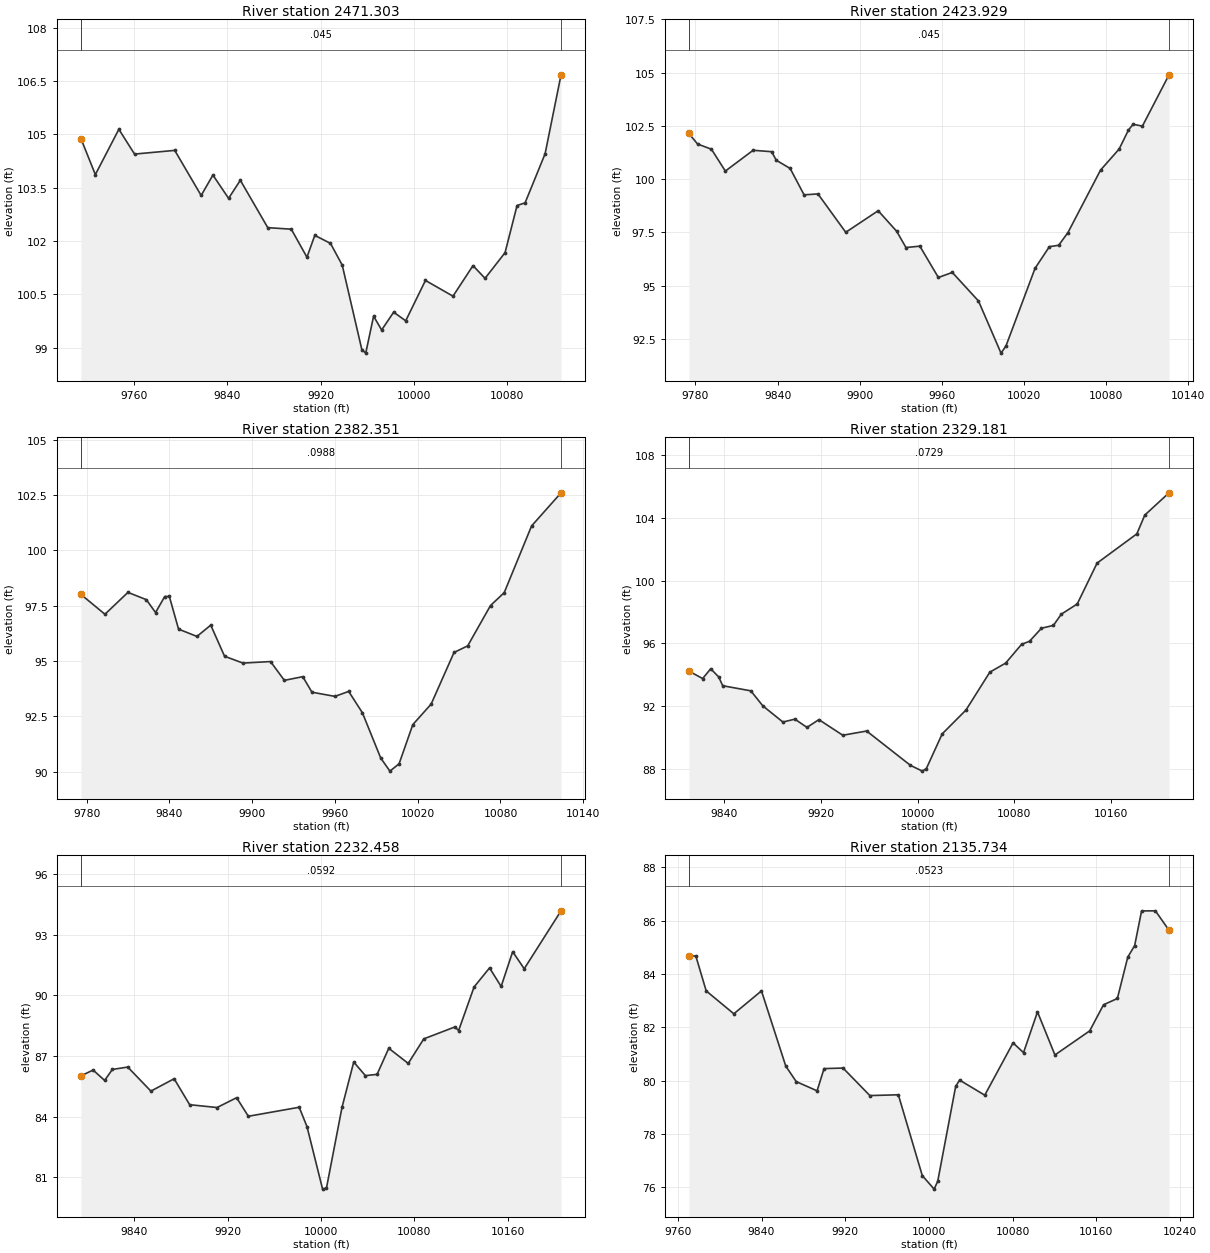
Type RM Length L Ch R = 1 ,2471.303,47.374000,47.374000,47.374000
XS GIS Cut Line= 6
1266188.28555512616794.9466153091265944.36194399616741.127170846
1265911.10837445616751.6102618871265909.13094339616751.909872726
 1265879.5674676616758.697424814 1265789.1466347616786.651384473
#Sta/Elev= 30
9714.343104.88119726.712103.8685 9746.87105.14149760.309104.44489794.786104.5486
9817.425103.28159827.504103.85559840.943103.20149851.022103.70839874.541102.3778
9894.699102.33429908.138101.54699914.858102.16049928.296101.93639938.376 101.325
9955.17498.952689958.534 98.8516 9965.2899.89028 9972.1699.50169 9982.48100.0021
  9992.899.7595410009.74 100.89410033.34100.452110050.51101.310910060.81100.9528
10077.98101.674510088.28102.999810095.15103.073510112.32104.454110125.98106.6718
#Mann= 3 , 0 , 0
9714.343   0.045       09714.343   0.045       010125.98   0.045       0
#XS Ineff= 2 , 0
       09969.414        10037.63       0
Bank Sta=9714.343,10125.98
Exp/Cntr=0.3,0.1

Type RM Length L Ch R = 1 ,2423.929,41.578700,41.578700,41.578700
XS GIS Cut Line= 6
1266110.16055512616741.9952263981265924.39666623616695.120226398
1265911.76841837616699.3997874861265881.09471497616713.609714881
 1265858.7705093616721.9076054391265773.57893994 616744.89146854
#Sta/Elev= 30
9775.181102.13959781.506101.64649791.657101.40159801.808100.3757 9822.11 101.352
9835.644101.28469839.028 100.8849849.179100.4977 9859.3399.260829869.48199.30304
9889.78397.502469913.46998.514789927.00497.550319933.77196.787379943.92296.85243
9957.45795.381749967.62895.619469986.76694.2786610003.2291.8319510006.8492.16644
10028.0895.8108510038.5696.8277310045.3696.8934710052.1597.4922610075.94100.4222
10089.53  101.4110096.33102.300310099.73102.572510106.52102.484810125.96104.8927
#Mann= 3 , 0 , 0
9775.181   0.045       09775.181   0.045       010125.96   0.045       0
#XS Ineff= 2 , 0
       09970.068         10038.3       0
Bank Sta=9775.181,10125.96
Exp/Cntr=0.3,0.1

Type RM Length L Ch R = 1 ,2382.351,53.169400,53.169400,53.169400
XS GIS Cut Line= 6
1266101.47999954616695.1202263981265920.25698167616662.174884558
1265883.81828025616667.5962065311265881.87799531616668.081277847
1265842.24080244616674.2783166171265758.05612254616685.111021414
#Sta/Elev= 30
9775.85798.011879793.27497.114659809.94798.104419823.28697.774159829.95597.19278
9836.62497.916289839.95997.920049846.62896.442599859.96696.11184 9869.9796.62372
9879.97495.216439893.31394.90686 9913.3294.976139923.32494.125929936.66294.29279
9943.33293.590169960.00593.401159969.95693.626189979.90792.658979993.174 90.6142
9999.84890.0217410006.49 90.353110016.4592.1258710029.7393.0523110046.3195.38699
10056.2395.6861410072.7797.51021 10082.798.0911110102.54101.107910123.89102.6053
#Mann= 3 , 0 , 0
9775.857  0.0988       09775.857  0.0988       010123.89  0.0988       0
#XS Ineff= 2 , 0
       09964.394        10042.01       0
Bank Sta=9775.857,10123.89
Exp/Cntr=0.3,0.1

Type RM Length L Ch R = 1 ,2329.181,96.723700,96.723700,96.723700
XS GIS Cut Line= 6
1266069.36194399616639.1306430551265971.70569399616623.939670846
1265879.99344432616615.9712509511265877.99964803   616616.128656
1265802.02861664616619.9858280121265673.93399891616629.485062107
#Sta/Elev= 30
9810.76894.233389822.169 93.75969828.80994.38339 9835.4593.86234 9838.7793.30185
9862.01292.976159871.97392.017689888.57490.986359898.53591.170269908.49690.64364
9918.38591.139919938.14490.144169957.90390.413099994.12888.2251910004.0187.85551
10007.2988.0147510020.4390.2294610040.1491.7532210059.8594.1661310072.9994.74618
10086.1495.9418110092.72 96.136210102.5996.9685810112.4697.1474110119.0497.86525
 10132.298.5138810148.65 101.12210181.55102.986810188.13104.182810208.17 105.603
#Mann= 3 , 0 , 0
9810.768  0.0729       09810.768  0.0729       010208.17  0.0729       0
#XS Ineff= 2 , 0
       09943.778        10056.42       0
Bank Sta=9810.768,10208.17
Exp/Cntr=0.3,0.1

Type RM Length L Ch R = 1 ,2232.458,96.723600,96.723600,96.723600
XS GIS Cut Line= 6
1266098.00340251616554.0580564051266009.72191781616543.932537495
1265910.38065753616523.5436028471265801.85367605616504.224458914
1265746.75283494616497.0170677191265692.04984158616492.241691017
#Sta/Elev= 30
9794.49786.01893 9804.9286.307519814.80585.793949821.39586.336139834.57586.45512
  9854.485.265169874.287 85.87699887.58884.593859911.03384.454339927.77984.93966
9937.82684.021739981.366 84.4675 9988.0583.5045410001.3880.4189210004.7180.47493
10018.0484.4698610028.0486.7018110038.0486.0301210048.0386.0938210058.0387.38357
10074.6986.6354110088.0287.8489310114.5488.4360610117.8588.2620210131.0890.41577
10144.3291.3584410154.23 90.439210164.1192.1599110173.9991.3158810205.5194.18022
#Mann= 3 , 0 , 0
9794.497  0.0592       09794.497  0.0592       010205.51  0.0592       0
#XS Ineff= 2 , 0
       09926.474        10032.85       0
Bank Sta=9794.497,10205.51
Exp/Cntr=0.3,0.1

Type RM Length L Ch R = 1 ,2135.734,96.723700,96.723700,96.723700
XS GIS Cut Line= 6
1266159.82710281616477.1474771511266027.23773409616459.187849004
1265978.13919962616447.6013625171265861.28481762616412.427693892
1265799.80462384616401.2379316961265710.56610647616390.236680637
#Sta/Elev= 30
9770.59384.66779 9777.2284.672029787.12583.362939813.53682.503959839.947 83.3626
9863.17880.541949873.15679.960169893.11279.613299899.76480.447629917.91580.46846
9943.52379.43585 9970.7579.465439993.62776.4342810004.9575.92611 10008.476.22385
10025.5679.7845510029.2980.0166310053.3379.4503310080.3781.4128610090.3881.04638
10103.7282.5758710120.3980.9595710153.6181.8630610166.8482.8435810180.06 83.0778
10189.9884.6279110196.5985.06374 10203.286.3631310216.4286.36669 10229.485.63798
#Mann= 3 , 0 , 0
9770.593  0.0523       09770.593  0.0523       0 10229.4  0.0523       0
#XS Ineff= 2 , 0
       09943.456        10042.13       0
Bank Sta=9770.593,10229.4
Exp/Cntr=0.3,0.1

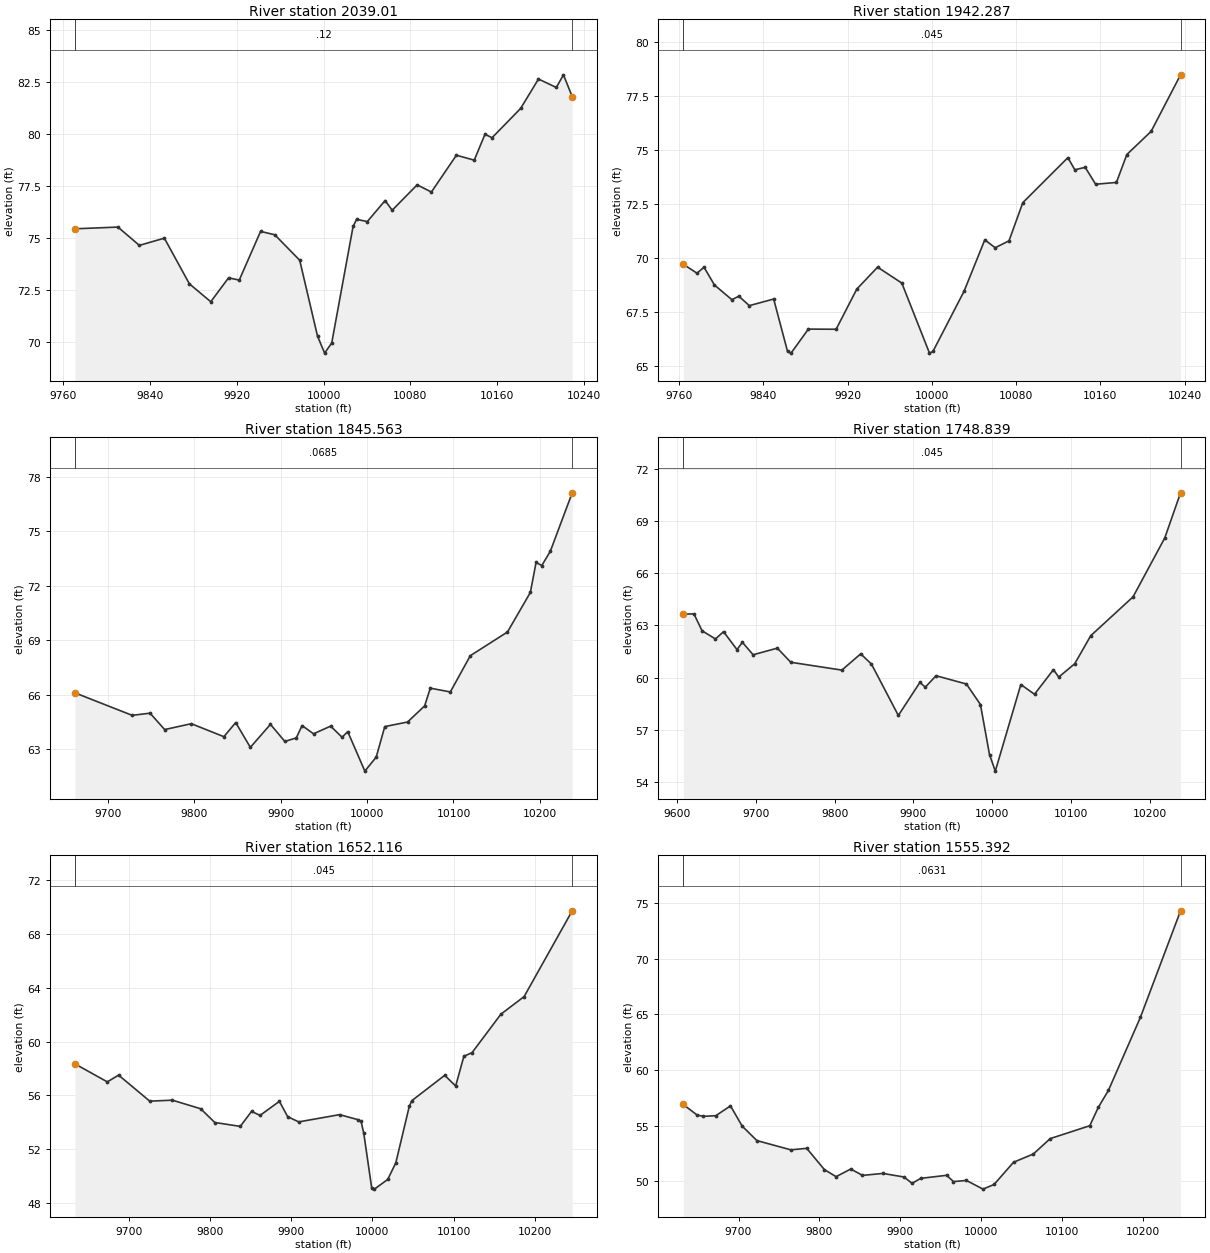
Type RM Length L Ch R = 1 , 2039.01,96.723600,96.723600,96.723600
XS GIS Cut Line= 6
1266166.52627553616352.9672499251266043.74655049616341.467111824
1265938.68834892616338.4794751241265936.68834892616338.479475182
1265864.92761108616336.4164797321265708.85863345 616323.04826439
#Sta/Elev= 30
9770.58275.445869810.28775.528959830.05874.649429853.12574.995939876.19172.80175
9895.95471.938649912.36573.089319922.21172.979039941.90475.322319955.033  75.158
9978.00873.933059994.41970.2881810000.9869.4679110007.5569.9556310027.2475.55736
10030.5275.9001710040.3775.7940210056.7876.8032310063.3476.3395110086.3677.55908
10099.5377.2150110122.5878.9842610139.0578.7467310148.9379.9887110155.51 79.8269
10181.8681.2357210198.3282.6472610214.7882.2415610221.3782.8500110229.4381.80084
#Mann= 3 , 0 , 0
9770.582    0.12       09770.582    0.12       010229.43    0.12       0
#XS Ineff= 2 , 0
       09943.726        10034.19       0
Bank Sta=9770.582,10229.43
Exp/Cntr=0.3,0.1

Type RM Length L Ch R = 1 ,1942.287,96.723700,96.723700,96.723700
XS GIS Cut Line= 6
1266172.78120744616261.5035727681266092.24378068616251.015647892
1266034.15178784616245.678065895 1265938.6883461616241.755820578
1265850.08425149616238.7796783011265702.14590013616226.504209642
#Sta/Elev= 30
9763.90269.72292 9776.9969.305799783.60769.585089793.53368.760369810.07568.07874
9816.69268.241139826.61867.803369849.75868.109969862.93765.680099866.23165.60383
9882.70566.717159909.04366.709639928.74568.574179948.44669.586369971.432 68.8492
  9997.765.6051810000.9865.6808810030.5368.4689710050.22 70.851910060.0770.48656
 10073.270.8054710086.3372.5749310129.13 74.660210135.7174.0975210145.5974.21043
10155.4673.4280610175.2273.5112510185.0974.8039410208.1475.87546 10236.178.49634
#Mann= 3 , 0 , 0
9763.902   0.045       09763.902   0.045       0 10236.1   0.045       0
#XS Ineff= 2 , 0
       09938.895        10055.13       0
Bank Sta=9763.902,10236.1
Exp/Cntr=0.3,0.1

Type RM Length L Ch R = 1 ,1845.563,96.723600,96.723600,96.723600
XS GIS Cut Line= 6
1266272.48694399616222.029948622 1266083.3622905 616165.01093398
1266003.89695859616151.7203713951265944.91938251616145.326626003
1265872.36837506616138.2568477691265708.21234921616116.302451804
#Sta/Elev= 30
9661.57566.092769727.86864.853219748.60964.972039765.562 64.06889796.40264.39299
9834.09663.677329847.80364.455029864.76663.08983 9888.0564.357289904.68263.41638
9917.98863.610749924.64164.289029937.94763.836499957.76164.259159970.961 63.6457
9977.56163.954989997.36161.7797910010.5562.5543110020.4464.2334910046.8164.48408
10066.5965.3723310073.1966.3496910096.3666.1419310119.53 68.139610162.5669.44433
10189.0471.6218510195.6673.2747210202.2873.1055910212.2173.8961810237.5177.11028
#Mann= 3 , 0 , 0
9661.575  0.0685       09661.575  0.0685       010237.51  0.0685       0
#XS Ineff= 2 , 0
       09936.556        10026.62       0
Bank Sta=9661.575,10237.51
Exp/Cntr=0.3,0.1

Type RM Length L Ch R = 1 ,1748.839,96.723700,96.723700,96.723700
XS GIS Cut Line= 6
1266340.19527733616169.9466152941266027.12915158616079.054232463
1265992.12842211616065.399745807 1265940.8121469616039.810508355
1265905.44660929616027.4554259931265736.65704194615988.766294733
#Sta/Elev= 30
 9607.7663.651139621.366 63.66469631.61262.693379648.688 62.22039658.93462.64185
 9676.0161.605479682.84162.028679696.50261.30965 9727.2461.691029744.316 60.8779
9809.207  60.4269833.11461.363759846.77560.772859880.92857.814689908.29959.71658
9915.14359.444819928.83160.102169967.42559.623959985.18158.444039996.70255.56024
10004.0554.6064410036.4959.5945210053.8759.0351410077.8860.4500210084.6560.02561
10104.9560.7928610125.2562.4068210179.0364.6475510219.2868.0394710239.3370.63876
#Mann= 3 , 0 , 0
 9607.76   0.045       0 9607.76   0.045       010239.33   0.045       0
#XS Ineff= 2 , 0
       0 9938.33        10028.05       0
Bank Sta=9607.76,10239.33
Exp/Cntr=0.3,0.1

Type RM Length L Ch R = 1 ,1652.116,96.723600,96.723600,96.723600
XS GIS Cut Line= 6
1266338.45916623616065.7799486221266125.97491664615989.591457784
1266067.37567452615972.9391520321266022.70307103615964.498105049
1265928.55440232615953.8794330811265747.81517974615910.810493216
#Sta/Elev= 30
9633.40658.339349673.32956.997779687.27157.49995 9725.6155.562019753.49355.63378
9788.346 54.99579805.77353.971049837.14153.680949851.08354.800499861.48754.49935
9885.36355.548089895.59554.400499909.238 54.01669959.54954.556869982.69254.17312
9985.98754.066449989.28253.180099999.16749.0627910002.4549.0078610018.91  49.736
10028.8350.9739210045.4355.1882310048.7555.6085910089.0457.4861210102.5356.69044
10112.6558.8995310122.7759.1795810158.3362.0435110186.8563.3491710246.1269.73935
#Mann= 3 , 0 , 0
9633.406   0.045       09633.406   0.045       010246.12   0.045       0
#XS Ineff= 2 , 0
       09944.174        10043.78       0
Bank Sta=9633.406,10246.12
Exp/Cntr=0.3,0.1

Type RM Length L Ch R = 1 ,1555.392,96.723700,96.723700,96.723700
XS GIS Cut Line= 6
1266347.13972175616017.1688375031266109.78164849615905.725128368
1266043.83443126615877.7985942811265980.70995489615859.095002949
1265854.03844798615813.2513979081265778.08818561615788.039980978
#Sta/Elev= 30
9631.70856.908749648.81355.959149656.53255.842969671.94155.901459690.06456.78313
9704.56254.960899722.68453.665079764.60652.83527  9784.352.969589806.04751.06132
9820.54450.426129838.66751.112099853.16550.540529878.53650.715299904.42450.39434
9914.42649.825979925.11550.274369957.18150.547889965.54349.982599981.52350.08553
10002.0849.3059510015.7349.7235910039.8151.7200910064.2352.4593510085.1653.84607
10134.0155.0006710144.4856.6463410157.0558.1773210196.5364.7348310246.1374.29996
#Mann= 3 , 0 , 0
9631.708  0.0631       09631.708  0.0631       010246.13  0.0631       0
#XS Ineff= 2 , 0
       09938.344        10068.09       0
Bank Sta=9631.708,10246.13
Exp/Cntr=0.3,0.1

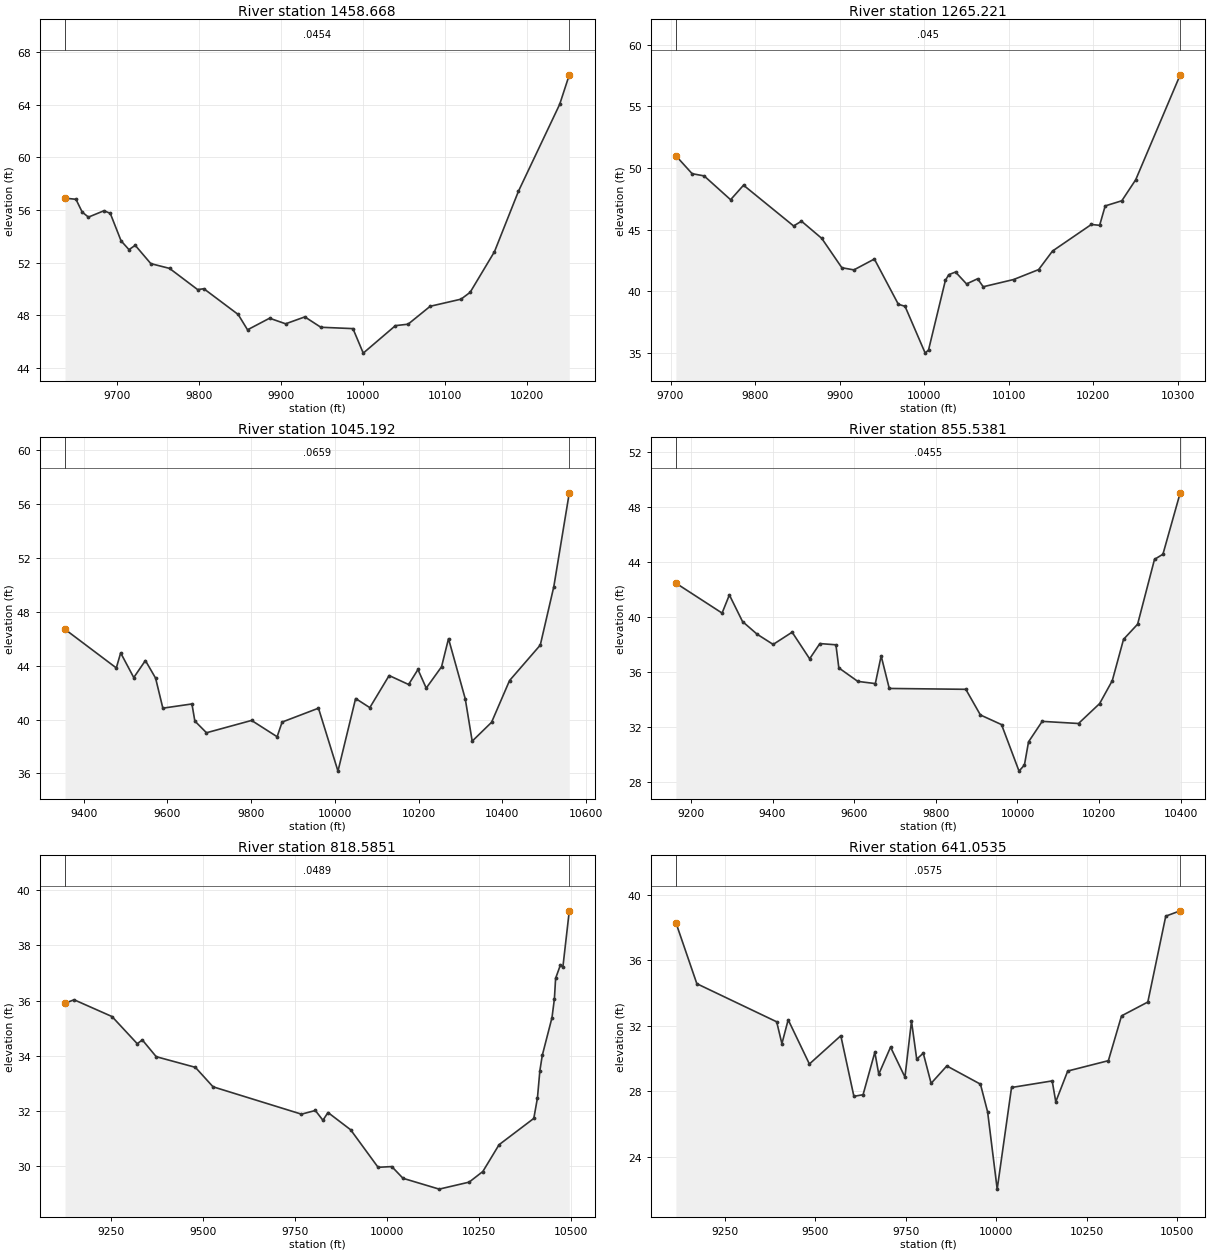
Type RM Length L Ch R = 1 ,1458.668,193.447300,193.447300,193.447300
XS GIS Cut Line= 6
1266371.44527733615975.5021708311266168.69476354615856.884323165
1266043.66159296615774.104036897 1265982.8815746615736.747341603
1265908.87082255615697.5947108421265840.66031006615667.639265493
#Sta/Elev= 30
 9636.9256.908789650.25756.819699657.859 55.84889665.461  55.4659684.46755.95083
9692.06955.750379705.24153.660879714.87552.990089722.47753.319969741.48251.92695
9764.28951.564869798.49849.952789806.10150.016979847.91248.059299859.315 46.8941
9886.18647.774949905.75147.350269929.12447.875469948.66947.086759987.76146.98415
10000.3145.1196110039.5147.2110510054.9147.3201310081.8748.68288 10119.449.22342
10130.53 49.742710160.2252.8387610189.4657.4401810239.6364.0412910251.36 66.2874
#Mann= 3 , 0 , 0
 9636.92  0.0454       0 9636.92  0.0454       010251.36  0.0454       0
#XS Ineff= 2 , 0
       09933.475                       0
Bank Sta=9636.92,10251.36
Exp/Cntr=0.3,0.1

Type RM Length L Ch R = 1 ,1265.221,220.028700,220.028700,220.028700
XS GIS Cut Line= 6
1266402.73868012615835.9188375031266376.69701338615808.792101383
1266304.56436875615744.2428468171266235.25319338615678.142232522
1266153.17270789 615619.990018071265887.33069399615617.819879174
#Sta/Elev= 30
9706.32750.983959725.49949.532389739.71149.351949771.03547.419849786.34448.59833
9845.61745.292379854.891 45.68069878.89344.286959902.66241.905689916.924 41.7299
9941.143 42.61089969.49238.943149977.442 38.776610001.2934.9803210005.2735.24267
10025.1440.8705510029.1241.3386210037.1541.55844 10050.240.5921510063.3341.01204
10069.8940.3617210105.9840.9505310135.5141.7542710151.9143.2580410197.8545.41208
10207.6945.3457910214.2546.9185710233.9447.3357410250.3449.03909   1030357.54837
#Mann= 3 , 0 , 0
9706.327   0.045       09706.327   0.045       0   10303   0.045       0
#XS Ineff= 2 , 0
       09924.504                       0
Bank Sta=9706.327,10303
Exp/Cntr=0.3,0.1

Type RM Length L Ch R = 1 ,1045.192,189.654300,189.654300,189.654300
XS GIS Cut Line= 6
1266957.93954876615719.9177570641266380.37878487615519.483729288
1266266.28299671615456.8437546941266157.06362271 615477.51943402
1266141.87265053615568.665267363 1265890.1365394615597.962142348
#Sta/Elev= 30
9355.59146.703379478.08543.836789488.50444.952829519.75943.122529547.54144.38631
9571.87743.080569589.21440.84978 9658.6741.163039665.61539.894029693.39839.02393
9801.05439.939159862.07938.728659873.98239.817599960.80240.8487810007.35 36.1755
10049.4841.5672910083.3740.8892810129.5243.2731410175.9742.6074910198.3143.72096
10218.0642.3407310254.65 43.921810271.2846.0106810311.3141.5367310327.8238.39957
10374.0739.80002   1041742.8990210490.3945.53304 10522.749.8698110559.6856.83748
#Mann= 3 , 0 , 0
9355.591  0.0659       09355.591  0.0659       010559.68  0.0659       0
#XS Ineff= 2 , 0
       09955.967        10044.03       0
Bank Sta=9355.591,10559.68
Exp/Cntr=0.3,0.1

Type RM Length L Ch R = 1 ,855.5381,36.953000,36.953000,36.953000
XS GIS Cut Line= 6
1267050.99510431615666.2719237061266341.35968769 615359.19727093
1266308.42709395615353.6319491421266285.14475602615354.014312342
 1266187.4368445615372.7787628171265896.48121545615466.619145945
#Sta/Elev= 30
9163.29742.47534 9276.3940.296329294.264 41.61829326.43739.680859362.185 38.7568
9401.50938.011819447.98138.903719490.87936.963699515.90338.074359555.22637.98483
9562.37636.302169608.84835.319019651.74635.159599666.04637.173579685.92134.80484
9873.38634.742129909.13432.87345 9960.9432.1707710003.7828.7818310017.01 29.2309
10027.0230.9146610060.5132.4076510149.4332.2515510201.1433.7014610232.1635.37198
10259.7438.3846910294.2139.4854110335.58 44.208910356.2644.5843410398.5349.05622
#Mann= 3 , 0 , 0
9163.297  0.0455       09163.297  0.0455       010398.53  0.0455       0
#XS Ineff= 2 , 0
       09954.874        10060.15       0
Bank Sta=9163.297,10398.53
Exp/Cntr=0.3,0.1

Type RM Length L Ch R = 1 ,818.5851,177.531600,177.531600,177.531600
XS GIS Cut Line= 4
1267111.92473385615568.6652673631266385.84753492615347.261507049
1265903.15737271 615223.613184021265791.39521998615232.293739587
#Sta/Elev= 30
9125.10735.907249149.828 36.03239252.728 35.42549321.32734.441089335.04734.57887
9372.77733.971639479.10633.586259527.12532.881179767.22431.890249804.95332.02368
9825.53331.669069839.25331.950199900.78131.32524 9975.29 29.966110012.5429.99234
10043.0329.5678110141.24 29.175910222.5229.4291110259.7829.8140710303.8130.78379
10398.1831.7368710408.0532.4755410414.63 33.461710421.2134.0205710447.5435.38293
10454.1236.0636310457.4136.8092510470.5737.2971110477.1537.2173710494.57 39.2532
#Mann= 3 , 0 , 0
9125.107  0.0489       09125.107  0.0489       010494.57  0.0489       0
#XS Ineff= 2 , 0
       09954.854        10066.51       0
Bank Sta=9125.107,10494.57
Exp/Cntr=0.3,0.1

Type RM Length L Ch R = 1 ,641.0535,168.665500,168.665500,168.665500
XS GIS Cut Line= 4
1267016.06694978615496.863571301 1266263.4627831615149.207321316
 1266132.1070255615163.9343645721265703.50459495615211.677420139
#Sta/Elev= 30
 9115.3138.311129173.09634.581829393.54832.253959408.00430.918079425.32632.37654
9483.89729.675059570.63231.403839606.77227.70112 9632.0727.798699664.59530.39345
9675.437 29.05249707.963 30.70729747.71628.875649765.78632.292599780.24229.97352
9798.31230.336089819.99628.493789863.36329.557229956.20228.443359976.01126.74872
10002.4222.0306110042.0428.2403710154.2828.6426310164.1827.3682110197.1929.24605
10309.4329.8786710345.7432.6159310418.3733.4615910467.8938.7101310507.7639.03406
#Mann= 3 , 0 , 0
 9115.31  0.0575       0 9115.31  0.0575       010507.76  0.0575       0
#XS Ineff= 2 , 0
       09952.059        10058.17       0
Bank Sta=9115.31,10507.76
Exp/Cntr=0.3,0.1

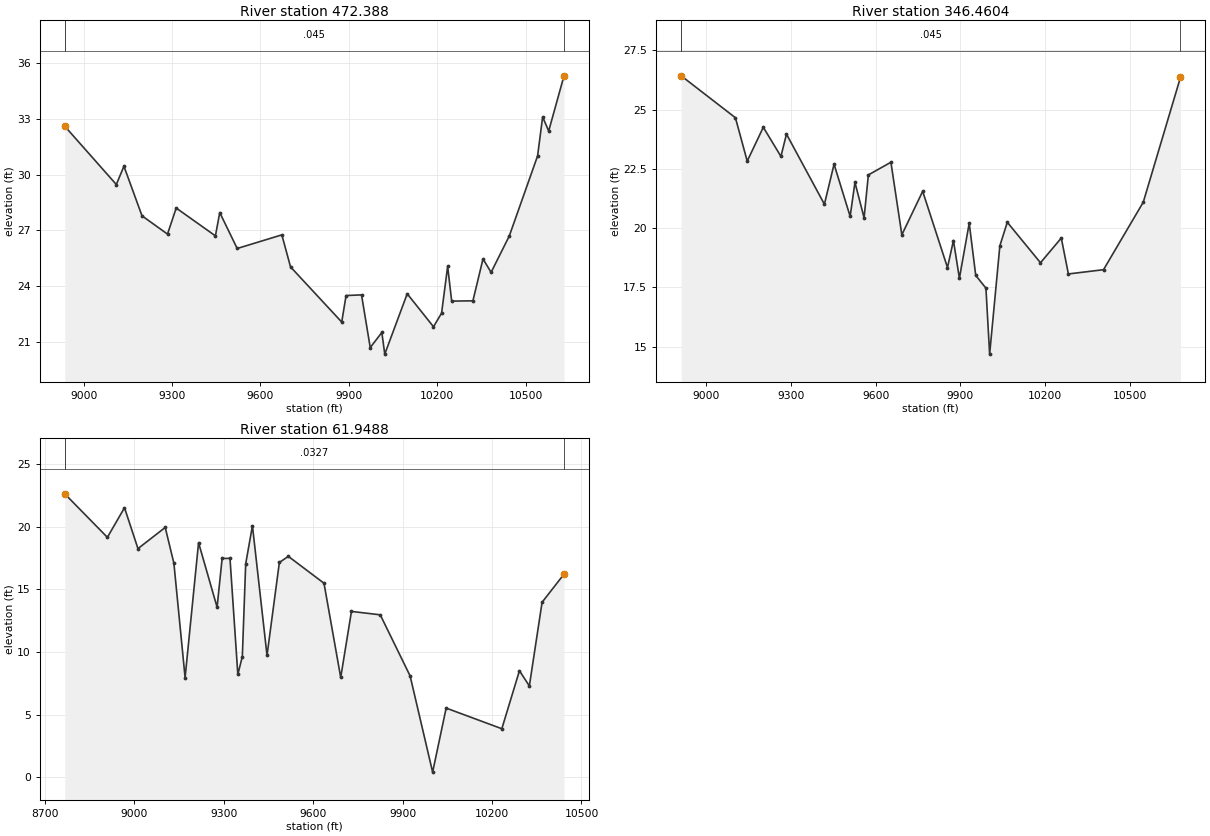
Type RM Length L Ch R = 1 , 472.388,125.927600,125.927600,125.927600
XS GIS Cut Line= 6
1267112.42111647615448.2524601821266239.15722755614995.127460182
 1266158.3397001614995.8225260971266156.34700683614995.993328422
1266071.45469528 615004.382958771265552.35167205615162.922599077
#Sta/Elev= 30
8935.88832.603739110.93529.470349136.80930.452529198.09627.788819284.65726.80625
9314.22728.206579447.29126.710929462.07527.962119521.21526.032389672.75926.76457
9702.32925.043499876.051 22.07949890.83623.504089943.29423.539349972.82320.70663
10012.2521.5208410022.1420.3555310098.3823.5990410187.5721.8269710215.0122.55725
10235.5925.0696710249.3223.2048210321.3523.2201310355.6625.47275 10383.124.75026
10444.8526.70519 10540.931.0062810558.0533.0994710578.6432.3487310630.6135.31186
#Mann= 3 , 0 , 0
8935.888   0.045       08935.888   0.045       010630.61   0.045       0
#XS Ineff= 2 , 0
       09935.771        10053.28       0
Bank Sta=8935.888,10630.61
Exp/Cntr=0.3,0.1

Type RM Length L Ch R = 1 ,346.4604,284.511600,284.511600,284.511600
XS GIS Cut Line= 6
1267155.82389423615333.6691268381266553.39333868614984.710793525
1266256.51833868614871.8635713161266063.34727752614880.452521905
1265971.79611644614906.5857935251265547.14333865 615091.74204351
#Sta/Elev= 30
8912.58226.419769104.38624.652799146.09222.824339202.96524.251479265.28523.02342
9284.92123.96322 9419.0821.007739453.20422.694499510.07620.496159527.10621.92794
9559.36620.434969574.53222.244089654.29322.777029692.90119.718369766.60821.55288
9854.35518.338939875.41419.478829896.47317.887289931.234 20.20989954.20518.00918
9990.30117.4706910003.4314.6903310039.58 19.256410065.88 20.248110183.2418.54148
10256.8519.58322 10281.918.0694510406.1718.2488710546.7621.0946210678.2526.35373
#Mann= 3 , 0 , 0
8912.582   0.045       08912.582   0.045       010678.25   0.045       0
#XS Ineff= 2 , 0
       09945.471        10069.56       0
Bank Sta=8912.582,10678.25
Exp/Cntr=0.3,0.1

Type RM Length L Ch R = 1 , 61.9488,0.000000,0.000000,0.000000
XS GIS Cut Line= 6
1267164.50444975615213.8774601821266498.26072931614839.014979273
1266324.64961824614700.1260903921266123.91177103614610.065326497
1266004.55413207614654.553173706  1265743.052396614863.971576497
#Sta/Elev= 30
 8766.7122.616128909.70319.146128967.10921.507379012.28218.248669103.73219.93489
9132.74617.089279170.3917.9623779215.56518.720069277.689  13.576 9294.62 17.4627
9320.97117.470519347.3238.2144489362.381 9.643869373.67417.035839396.26120.07004
  9445.29.7334369486.60917.144039516.72517.630669636.30915.487649692.4197.974552
9728.43213.241529825.00512.968949925.1218.101434 10000.7 0.42704 10046.15.532987
10232.843.88751710291.958.51161510325.147.29649210367.89 13.969710441.4216.21392
#Mann= 3 , 0 , 0
 8766.71  0.0327       0 8766.71  0.0327       010441.42  0.0327       0
#XS Ineff= 2 , 0
       09925.922         10055.2       0
Bank Sta=8766.71,10441.42
Exp/Cntr=0.3,0.1